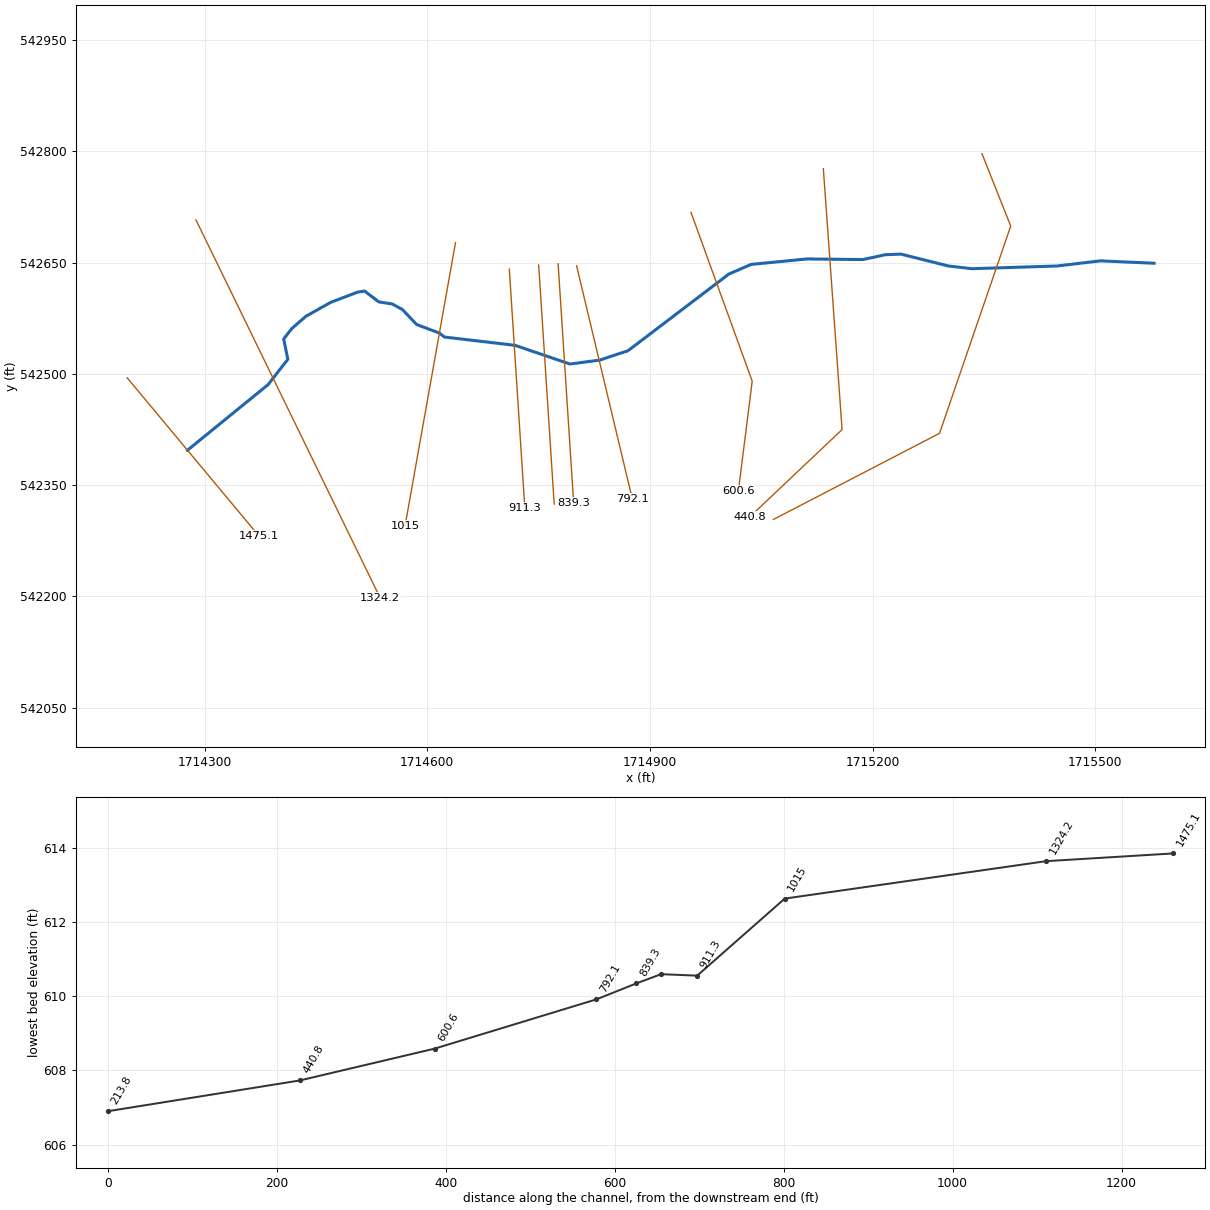
--- MCauslanRn.prj (project) ---

Proj Title=MCauslanRn
Current Plan=p01
Default Exp/Contr=0,0
English Units
Geom File=g01
Flow File=f01
Plan File=p01
BEGIN DESCRIPTION:
AMEC Environment & Infrastructure, 2013
Projection: NAD 1983 State Plane West Virginia South FIPS 4702 (US Feet)
Vertical Datum: NAVD 1988
END DESCRIPTION:
DSS Export Rating Curves= 0
DSS Export Rating Curve Sorted= 0
DSS Export Volume Flow Curves= 0
DXF OffsetX= 0
DXF OffsetY= 0
DXF ScaleX= 0
DXF ScaleY= 0

--- MCauslanRn.p01 (plan) ---

Plan Title=Floodplain
Program Version=4.00
Geom File=g01
Flow File=f01
K Sum by GR=0
Std Step Tol=0.01
Critical Tol=0.01
Num of Std Step Trials=20
Max Error Tol=0.3
Flow Tol Ratio=0.001
Split Flow NTrial=30
Split Flow Tol=0.02
Split Flow Ratio=0.02
Log Output Level=0
Friction Slope Method=1
Unsteady Friction Slope Method=2
Unsteady Bridges Friction Slope Method=1
Global Log Level=0
CheckData=False
Run HTab=0
Run UNet=0
Run PostProcess=0
UNET Theta=0
UNET Theta Warmup=0
UNET ZTol=0
UNET ZSATol=0
UNET MxIter=0
UNET MaxInSteps=0
UNET DtIC=0
UNET DtMin=0
UNET MaxCRTS=0
UNET WFStab=0
UNET SFStab=0
UNET WFX=0
UNET SFX=0
UNET DSS MLevel=0
UNET DZMax Abort=0
UNET Convert EG Bridges=0
UNET Use Existing IB Tables=0
UNET Froude Limit=0
UNET Froude Power=0
Write IC File=0
Echo Input=False
Echo Output=False
Write Detailed=0

--- MCauslanRn.f01 (steady flow) ---

Flow Title=USGS Regress. Eqn. (2010) - Western-Plateaus
Program Version=4.00
Number of Profiles=1
Profile Names=P100yr
River Rch & RM=MCauslanRn,Main      ,1475.1
     953
River Rch & RM=MCauslanRn,Main      ,1015
     954
River Rch & RM=MCauslanRn,Main      ,911.3
     960
Boundary for River Rch & Prof#=MCauslanRn,Main      ,1
Up Type=0
Dn Type=3
Dn Slope=0.005327

--- MCauslanRn.g01 (geometry) ---

Geom Title=USGS 3m DEM
Program Version=4.10

River Reach=MCauslanRn      ,Main
Reach XY= 30
      1714277.01      542396.933     1714385.542      542485.291
     1714412.243      542519.493     1714406.688      542546.923
     1714417.451      542560.812     1714436.549      542577.479
     1714469.882      542596.229      1714506.34      542610.118
     1714515.715      542611.507     1714534.813      542596.923
     1714552.868      542594.146     1714566.757      542586.507
     1714585.854      542566.368      1714616.24      542554.989
     1714623.323      542549.555     1714718.376      542538.369
     1714792.312      542513.171     1714832.388      542518.484
     1714870.499      542531.052      1715006.37      542634.419
     1715036.325      542647.446     1715111.865      542654.831
     1715186.972      542653.967     1715216.927      542660.482
       1715238.2      542661.351     1715302.455      542645.292
     1715333.945      542641.662     1715448.327      542645.301
     1715506.936      542652.251     1715579.252      542649.031

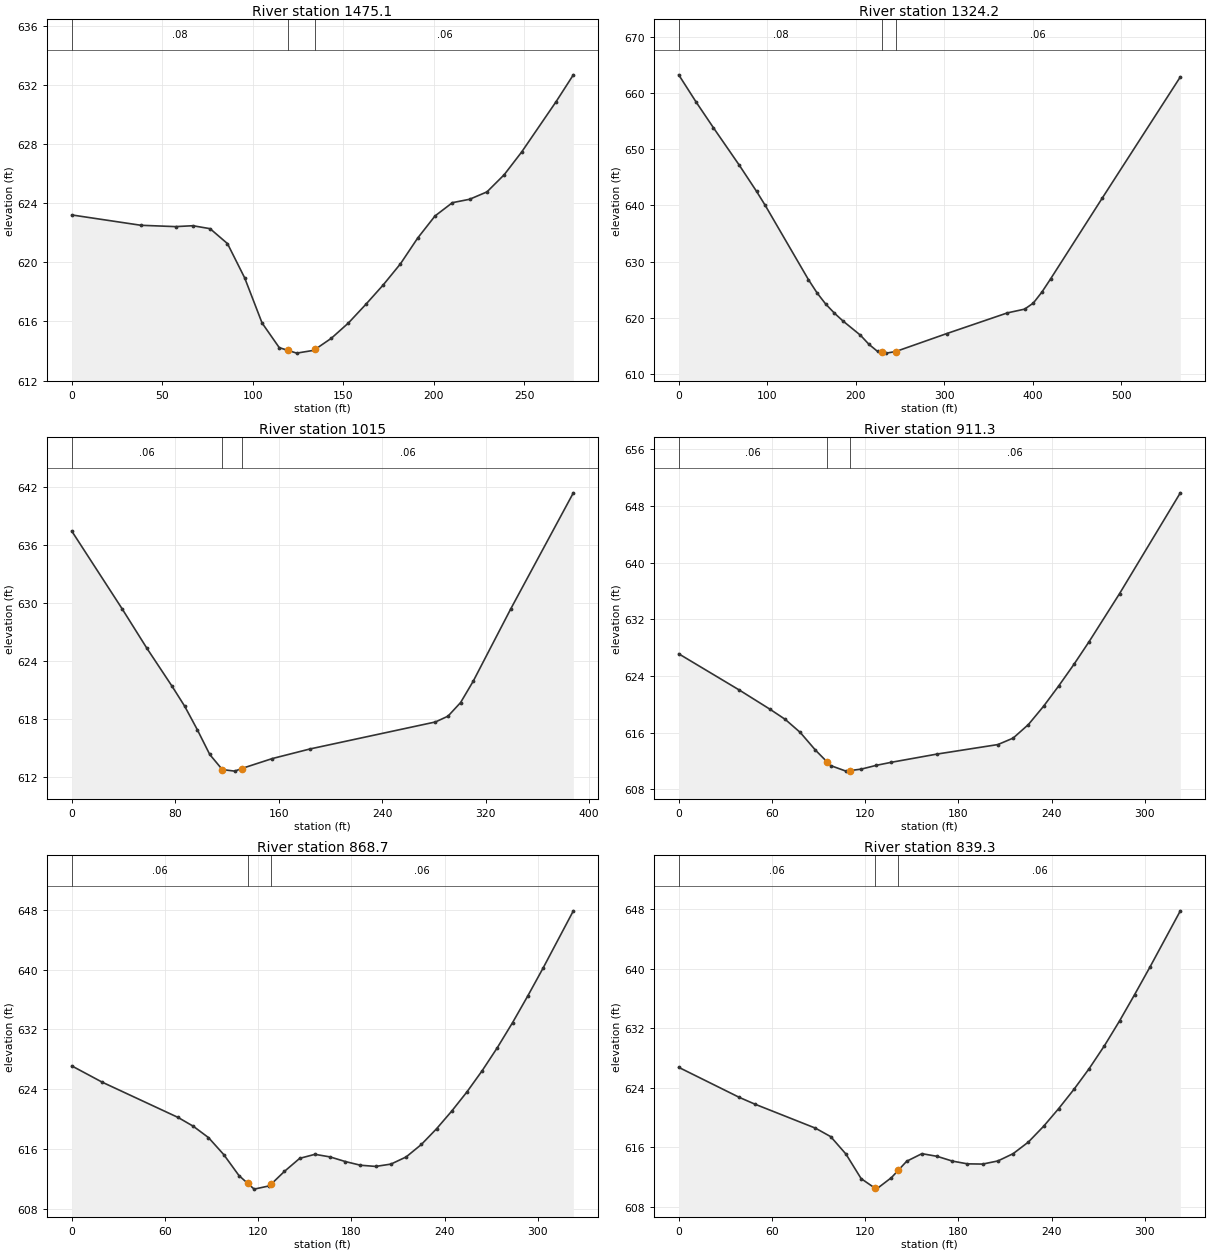
Type RM Length L Ch R = 1 ,1475.1  ,157.2,150.9,144.8
XS GIS Cut Line= 2
     1714195.779      542494.673     1714373.021      542281.774
#Sta/Elev= 27
       0  623.21    38.2  622.51    57.3  622.42    66.9  622.48    76.4  622.28
      86  621.27    95.5  618.95   105.1   615.9   114.6  614.23   119.6  614.04
   124.2  613.86   133.7  614.05   134.6  614.13   143.3  614.86   152.8   615.9
   162.4  617.16   171.9  618.46   181.5   619.9     191  621.64   200.6  623.14
   210.2  624.04   219.7  624.27   229.3  624.77   238.8  625.93   248.4  627.46
   267.5  630.88     277  632.69
#Mann= 3 , 0 , 0
       0     .08       0   119.6    .045       0   134.6     .06       0
Bank Sta=119.6,134.6
XS Rating Curve= 0 ,0
Exp/Cntr=0.3,0.1

Type RM Length L Ch R = 1 ,1324.2  ,322.9,309.2,294.1
XS GIS Cut Line= 2
     1714288.479      542707.473     1714536.732      542197.734
#Sta/Elev= 25
       0  663.31    19.6  658.47    39.1   653.9    68.4   647.2      88  642.51
    97.8  640.01   146.6  626.77   156.4  624.39   166.2   622.4     176  620.78
   185.7  619.38   205.3  616.86   215.1  615.21   224.8  613.95   230.2  613.78
   234.6  613.65   245.2  613.93     303  617.14   371.5  620.83     391   621.5
   400.8  622.58   410.6  624.56   420.4  626.91     479  641.38     567  662.94
#Mann= 3 , 0 , 0
       0     .08       0   230.2    .045       0   245.2     .06       0
Bank Sta=230.2,245.2
XS Rating Curve= 0 ,0
Exp/Cntr=0.3,0.1

Type RM Length L Ch R = 1 ,1015    ,97.7,103.6,108.5
XS GIS Cut Line= 2
     1714638.144      542676.788     1714570.193      542294.945
#Sta/Elev= 18
       0  637.44    38.8  629.44    58.2  625.31    77.6   621.4    87.3  619.35
      97  616.94   106.7  614.36   116.4   612.8     126  612.64   131.4  612.91
   155.1  613.94   184.2  614.93   281.2  617.72   290.9  618.32   300.6  619.72
   310.3  621.91   339.4   629.4   387.8  641.39
#Mann= 3 , 0 , 0
       0     .06       0   116.4    .045       0   131.4     .06       0
Bank Sta=116.4,131.4
XS Rating Curve= 0 ,0
Exp/Cntr=0.3,0.1

Type RM Length L Ch R = 1 ,911.3   ,42.6,42.7,43.1
XS GIS Cut Line= 2
     1714710.641      542641.141      1714731.55      542319.021
#Sta/Elev= 23
       0  627.12    39.1  621.99    58.7   619.3    68.5  617.87    78.2  616.02
      88  613.52    95.3   611.9    97.8  611.34   107.6  610.56   110.3  610.64
   117.4  610.84   127.2  611.38   136.9  611.81   166.3  612.97   205.4  614.31
   215.2  615.22     225  617.13   234.8  619.72   244.5  622.58   254.3  625.62
   264.1  628.84   283.7  635.62   322.8  649.84
#Mann= 3 , 0 , 0
       0     .06       0    95.3    .045       0   110.3     .06       0
Bank Sta=95.3,110.3
XS Rating Curve= 0 ,0
Exp/Cntr=0.3,0.1

Type RM Length L Ch R = 1 ,868.7   ,28.4,29.4,28.4
XS GIS Cut Line= 2
     1714750.198      542646.553     1714771.107      542324.432
#Sta/Elev= 30
       0   627.1    19.6  624.92    68.5  620.19    78.2  619.02      88   617.5
    97.8  615.23   107.6  612.42   113.3  611.36   117.4   610.6   127.2  611.04
   128.3  611.26   136.9  612.98   146.7  614.72   156.5  615.26   166.3  614.91
   176.1  614.29   185.8   613.8   195.6  613.64   205.4  613.95   215.2  614.91
     225  616.58   234.8  618.69   244.5  621.04   254.3  623.61   264.1  626.45
   273.9  629.55   283.7   632.9   293.4  636.44   303.2  640.15   322.8  647.86
#Mann= 3 , 0 , 0
       0     .06       0   113.3    .045       0   128.3     .06       0
Bank Sta=113.3,128.3
XS Rating Curve= 0 ,0
Exp/Cntr=0.3,0.1

Type RM Length L Ch R = 1 ,839.3   ,43.7,47.2,50.9
XS GIS Cut Line= 2
     1714776.397      542648.253     1714797.305      542326.133
#Sta/Elev= 29
       0  626.73    39.1  622.68    48.9  621.79      88  618.55    97.8  617.41
   107.6  615.07   117.4  611.76   126.3  610.48   127.2  610.35   136.9   611.9
   141.3  612.89   146.7   614.1   156.5  615.12   166.3  614.76   176.1  614.12
   185.8  613.75   195.6  613.72   205.4  614.14   215.2  615.12     225  616.68
   234.8   618.8   244.5  621.18   254.3  623.76   264.1  626.55   273.9  629.62
   283.7  632.98   293.4  636.52   303.2   640.2   322.8  647.78
#Mann= 3 , 0 , 0
       0     .06       0   126.3    .045       0   141.3     .06       0
Bank Sta=126.3,141.3
XS Rating Curve= 0 ,0
Exp/Cntr=0.3,0.1

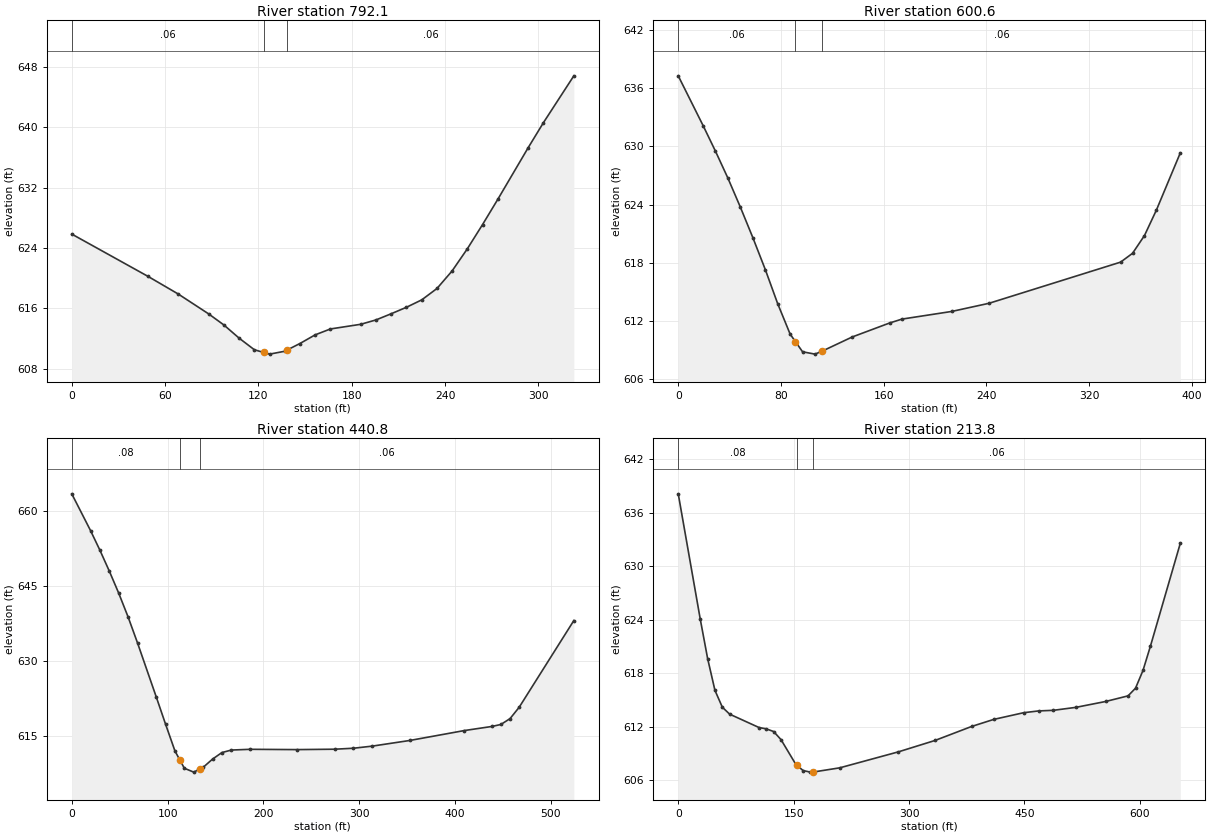
Type RM Length L Ch R = 1 ,792.1   ,188.9,191.5,193.7
XS GIS Cut Line= 2
     1714801.254      542645.665     1714876.253        542331.7
#Sta/Elev= 27
       0  625.85    48.9  620.25    68.5  617.89      88  615.26    97.8  613.79
   107.6  612.04   117.4   610.5   123.4  610.14   127.2  609.92   136.9   610.3
   138.4  610.46   146.7  611.33   156.5  612.48   166.3  613.26   185.8  613.88
   195.6  614.46   205.4  615.28   215.2  616.14     225  617.12   234.8  618.63
   244.5  620.95   254.3  623.89   264.1  627.11   273.9  630.46   293.4   637.3
   303.2  640.62   322.8  646.85
#Mann= 3 , 0 , 0
       0     .06       0   123.4    .045       0   138.4     .06       0
Bank Sta=123.4,138.4
XS Rating Curve= 0 ,0
Exp/Cntr=0.3,0.1

Type RM Length L Ch R = 1 ,600.6   ,165.7,159.8,153.6
XS GIS Cut Line= 3
     1714955.401      542717.615     1715037.847      542490.108
     1715019.284       542342.34
#Sta/Elev= 23
       0  637.27    19.4  632.13      29   629.5    38.7  626.72    48.4  623.73
    58.1  620.59    67.8   617.3    77.4   613.8    87.1  610.66    91.2 609.886
    96.8  608.83   106.5  608.59   112.2 608.907   135.5  610.36   164.6   611.8
   174.2   612.2     213  612.99     242  613.83   344.4  618.07   353.7  618.98
     363  620.81   372.3  623.44   390.9  629.33
#Mann= 3 , 0 , 0
       0     .06       0    91.2    .045       0   112.2     .06       0
Bank Sta=91.2,112.2
XS Rating Curve= 0 ,0
Exp/Cntr=0.3,0.1

Type RM Length L Ch R = 1 ,440.8   ,237,227.1,218.1
XS GIS Cut Line= 3
     1715133.688      542776.516     1715158.953      542424.807
     1715034.432      542307.001
#Sta/Elev= 30
       0  663.34    19.6  655.99    29.4  652.06    39.2  647.89      49  643.49
    58.8  638.73    68.6  633.56    88.2  622.74      98  617.25   107.7  611.95
     113 610.085   117.5   608.5   127.3  607.73     134  608.38   137.1  608.68
   146.9  610.33   156.7  611.64   166.5  612.14   186.1  612.29   235.1  612.23
   274.3  612.31   293.8   612.5   313.4  612.92   352.6  614.05   409.8  616.04
   438.3  616.85   447.8  617.25   457.4  618.42   466.9  620.68     524  638.02
#Mann= 3 , 0 , 0
       0     .08       0     113    .045       0     134     .06       0
Bank Sta=113,134
XS Rating Curve= 0 ,0
Exp/Cntr=0.3,0.1

Type RM Length L Ch R = 1 ,213.8   ,198,213.8,230.2
XS GIS Cut Line= 4
     1715347.406      542796.724     1715386.117      542699.123
     1715290.214      542419.767     1715066.406      542303.638
#Sta/Elev= 30
       0   638.1    28.6  624.06    38.2  619.63    47.7  616.07    57.3  614.18
    66.8   613.4     105   611.9   114.5  611.75     124  611.45   133.6  610.54
   152.6   607.8   154.7 607.644   162.2  607.08   171.7   606.9   175.7 606.914
   209.8  607.38     286  609.17   333.7  610.45   381.3  612.02     410  612.81
   448.8  613.56   468.2  613.76   487.6  613.83   516.7  614.16   555.5  614.82
   584.6  615.45   594.3  616.31     604   618.3   613.7  621.03   652.5  632.56
#Mann= 3 , 0 , 0
       0     .08       0   154.7    .045       0   175.7     .06       0
Bank Sta=154.7,175.7
XS Rating Curve= 0 ,0
Exp/Cntr=0.3,0.1

Chan Stop Cuts=-1
Use User Specified Reach Order=0
Composite Channel Slope=5